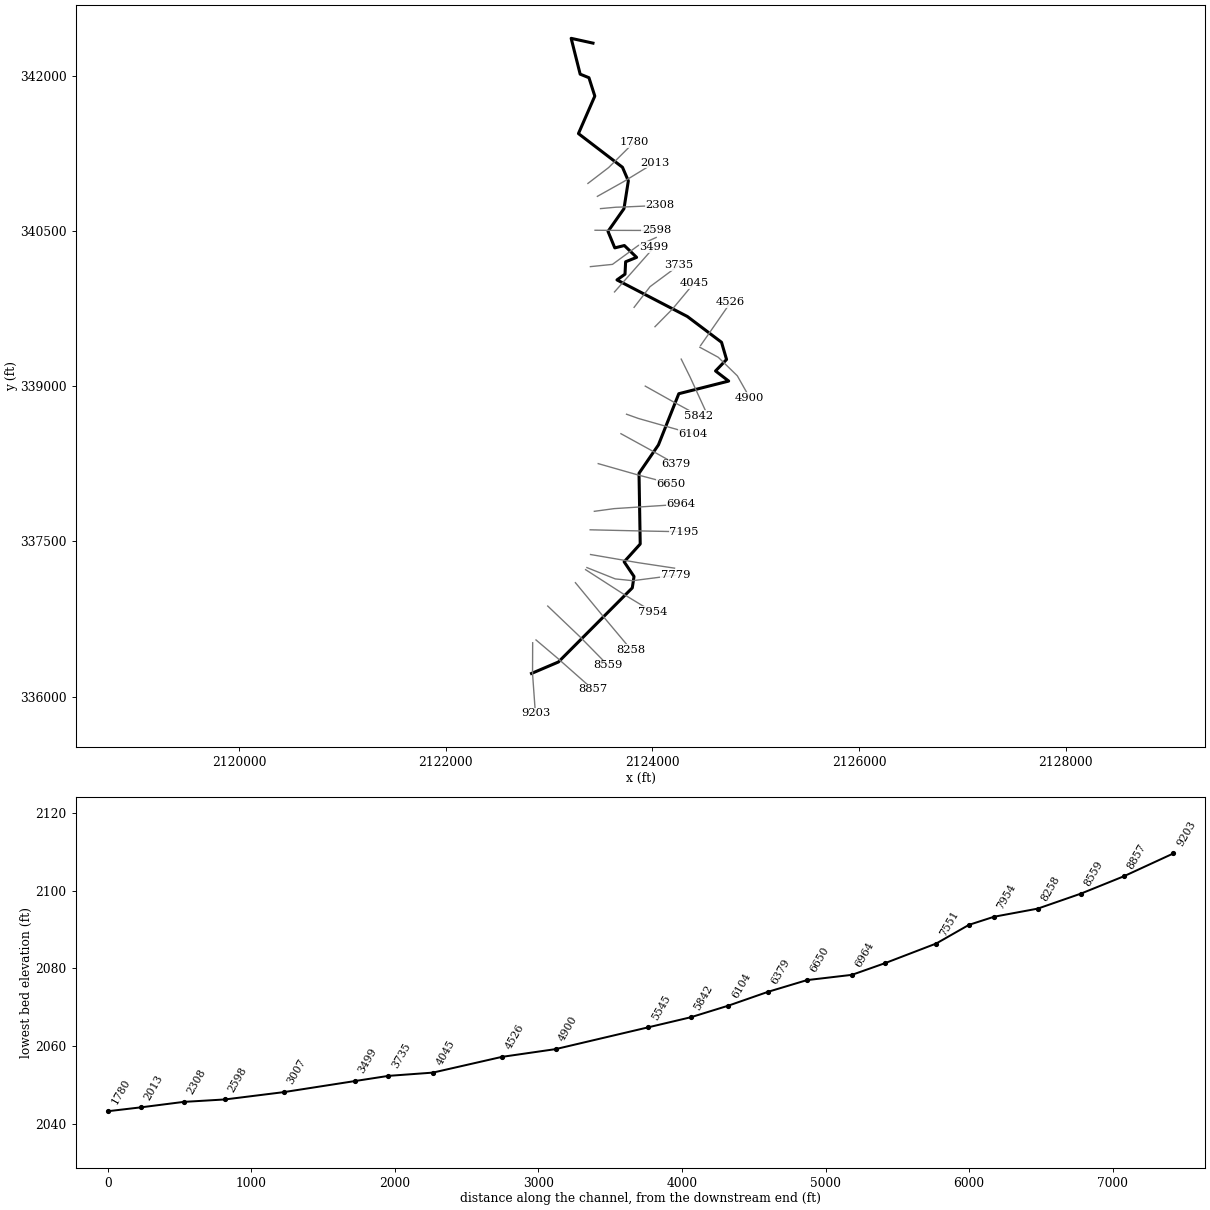
--- BURNSRN.prj (project) ---

Proj Title=BURNSRN
Current Plan=p01
Default Exp/Contr=0.3,0.1
English Units
Geom File=g01
Flow File=f01
Plan File=p01
Y Axis Title=Elevation
X Axis Title(PF)=Main Channel Distance
X Axis Title(XS)=Station
BEGIN DESCRIPTION:
Stream Name- Burns Run
Flood Zone: Zone A
Greenbrier County, WV
County-Wide Study
WVDHSEM-2018-3, Flood Risk Project
HEC-RAS Version: 5.0.7
General Notes:
For the Hydrology Regression was used.
END DESCRIPTION:
DSS Export Rating Curves= 0
DSS Export Rating Curve Sorted= 0
DSS Export Volume Flow Curves= 0
DXF Filename=BURNSRN.G2.
DXF OffsetX= 0
DXF OffsetY= 0
DXF ScaleX= 1
DXF ScaleY= 10

--- BURNSRN.p01 (plan) ---

Plan Title=Floodplain
Program Version=5.07
Short Identifier=Floodplain
Geom File=g01
Flow File=f01
Subcritical Flow
K Sum by GR= 0
Std Step Tol= 0.01
Critical Tol= 0.01
Num of Std Step Trials= 20
Max Error Tol= 0.3
Flow Tol Ratio= 0.001
Split Flow NTrial= 30
Split Flow Tol= 0.02
Split Flow Ratio= 0.02
Log Output Level= 0
Friction Slope Method= 1
Unsteady Friction Slope Method= 2
Unsteady Bridges Friction Slope Method= 1
Parabolic Critical Depth
Global Vel Dist= 0 , 0 , 0
Global Log Level= 0
CheckData=True
Encroach Param=-1 ,0,0, 0
Computation Interval=1MIN
Output Interval=1HOUR
Instantaneous Interval=1HOUR
Mapping Interval=1HOUR
Computation Time Step Use Courant=        0
Computation Time Step Use Time Series=    0
Computation Time Step Count To Double=0
Computation Time Step Max Doubling=0
Computation Time Step Max Halving=0
Computation Time Step Residence Courant=0
Run HTab= 0
Run UNet= 0
Run Sediment= 0
Run PostProcess= 0
Run WQNet= 0
Run RASMapper= 0
UNET Theta= 1
UNET Theta Warmup= 1
UNET ZTol= 0.02
UNET ZSATol= 0.02
UNET MxIter= 20
UNET Max Iter WO Improvement= 0
UNET MaxInSteps= 0
UNET DtIC= 0
UNET DtMin= 0
UNET MaxCRTS= 20
UNET WFStab= 2
UNET SFStab= 1
UNET WFX= 1
UNET SFX= 1
UNET 1D Methodology=Finite Difference
UNET DSS MLevel= 4
UNET Pardiso=0
UNET DZMax Abort= 100
UNET Use Existing IB Tables=-1
UNET Froude Reduction=False
UNET Froude Limit= 0.8
UNET Froude Power= 4
UNET D1 Cores= 0
UNET D2 Coriolis=0
UNET D2 Cores= 0
UNET D2 Theta= 1
UNET D2 Theta Warmup= 1
UNET D2 Z Tol= 0.01
UNET D2 Volume Tol= 0.01
UNET D2 Max Iterations= 20
UNET D2 Equation= 0
UNET D2 RampUpFraction=0.1
UNET D2 TimeSlices= 1
UNET D2 BCVolumeCheck=0
UNET D1D2 MaxIter= 0
UNET D1D2 ZTol=0.01
UNET D1D2 QTol=0.1
UNET D1D2 MinQTol=1
Write IC File= 0
Write IC File at Fixed DateTime=0
Write IC File at Sim End=0
Echo Input=False
Echo Parameters=False
Echo Output=False
Write Detailed= 0
HDF Write Warmup=0
HDF Write Time Slices=0
HDF Flush=0
HDF Face Node Velocities=0
HDF Compression= 1
HDF Chunk Size= 1
HDF Spatial Parts= 1
HDF Use Max Rows=0
HDF Fixed Rows= 1
Calibration Method= 0
Calibration Iterations= 20
Calibration Max Change=0.05
Calibration Tolerance=0.2
Calibration Maximum=1.5
Calibration Minimum=0.5
Calibration Optimization Method= 1
WQ AD Non Conservative
WQ ULTIMATE=-1
WQ Max Comp Step=1HOUR
WQ Output Interval=15MIN
WQ Output Selected Increments= 0
WQ Output face flow=0
WQ Output face velocity=0
WQ Output face area=0
WQ Output face dispersion=0
WQ Output cell volume=0
WQ Output cell surface area=0
WQ Output cell continuity=0
WQ Output cumulative cell continuity=0
WQ Output face conc=0
WQ Output face dconc_dx=0
WQ Output face courant=0
WQ Output face peclet=0
WQ Output face adv mass=0
WQ Output face disp mass=0
WQ Output cell mass=0
WQ Output cell source sink temp=0
WQ Output nsm pathways=0
WQ Output nsm derived pathways=0
WQ Output MaxMinRange=-1
WQ Daily Max Min Mean=-1
WQ Daily Range=0
WQ Daily Time=0
WQ Create Restart=0
WQ Fixed Restart=0
WQ System Summary=0
WQ Write To DSS=0
WQ Use Fixed Temperature=0
Sorting and Armoring Iterations= 10
XS Update Threshold= 0.02
Bed Roughness Predictor= 0
Hydraulics Update Threshold= 0.02
Energy Slope Method= 1
Volume Change Method= 1
Sediment Retention Method= 0
XS Weighting Method= 0
Number of US Weighted Cross Sections= 1
Number of DS Weighted Cross Sections= 1
Upstream XS Weight=0
Main XS Weight=1
Downstream XS Weight=0
Number of DS XS's Weighted with US Boundary= 1
Upstream Boundary Weight= 1
Weight of XSs Associated with US Boundary= 0
Number of US XS's Weighted with DS Boundary= 1
Downstream Boundary Weight= 0.5
Weight of XSs Associated with DS Boundary= 0.5
Percentile Method= 0
Sediment Output Level= 3
Mass or Volume Output= 0
Output Increment Type= 1
Profile and TS Output Increment= 1
XS Output Flag= 0
XS Output Increment= 10
Write Gradation File= 0
Read Gradation Hotstart= 0
Write HDF5 File= 1
Write Binary Output= 1
Write DSS Sediment File= 0
SV Curve= 0
Specific Gage Flag= 0

--- BURNSRN.f01 (steady flow) ---

Flow Title=Flow
Program Version=5.07
Number of Profiles= 6
Profile Names=f1p,f10p,f4p,f2p,f02p,f1pplus
River Rch & RM=BURNSRN,Main            ,9203
     572     302     402     484     799     846
River Rch & RM=BURNSRN,Main            ,7195
     649     345     457     550     905     960
River Rch & RM=BURNSRN,Main            ,4526
    1220     661     867    1040    1670    1800
River Rch & RM=BURNSRNT1,Main            ,2875
     504     265     353     426     705     745
River Rch & RM=BURNSRNT1,Main            ,2198
     669     356     472     568     932     990
River Rch & RM=CLBRSNCKT1,Main            ,2948
     116    57.4    78.7    96.5     166     171
River Rch & RM=CLBRSNCKT1,Main            ,2280
     138    69.1    94.4     116     198     210
River Rch & RM=CLBRSNCKT1,Main            ,1216
     156    78.2     107     130     223     230
River Rch & RM=CLBRSNCKT1,Main            ,243
     178    89.6     122     149     253     300
River Rch & RM=CLBRSNCKT2,Main            ,5369
     223     114     154     187     317     330
River Rch & RM=CLBRSNCKT2,Main            ,3799
     483     253     338     408     676     714
River Rch & RM=INDIANCK,Main            ,11519
     313     162     218     264     443     463
River Rch & RM=INDIANCK,Main            ,9807
     520     274     365     440     728     769
River Rch & RM=INDIANCK,Main            ,8108
     581     307     409     492     812     860
River Rch & RM=INDIANCK,Main            ,6227
     647     344     456     549     902     958
River Rch & RM=LTROARCK,Main            ,4000
     648     344     456     549     903     958
River Rch & RM=MLGNCKTR5,Main            ,7678
     581     307     409     492     812     860
River Rch & RM=MLGNCKTR5,Main            ,5118
     654     347     461     554     911     967
River Rch & RM=MLGNCKTR5,Main            ,2636
     728     388     514     617    1010    1080
River Rch & RM=ROARINGCK,Main            ,17918
     544     287     382     461     761     805
River Rch & RM=ROARINGCK,Main            ,16996
     613     325     431     519     855     906
River Rch & RM=ROARINGCK,Main            ,14906
     713     380     504     605     992    1060
River Rch & RM=ROARINGCK,Main            ,11661
     864     464     612     734    1200    1280
River Rch & RM=ROARINGCK,Main            ,8657
     964     520     685     820    1330    1430
River Rch & RM=ROARINGCK,Main            ,4987
    1570     861    1120    1340    2150    2320
Boundary for River Rch & Prof#=BURNSRN,Main            , 1
Up Type= 0
Dn Type= 3
Dn Slope=0.0012
Boundary for River Rch & Prof#=BURNSRN,Main            , 2
Up Type= 0
Dn Type= 3
Dn Slope=0.0012
Boundary for River Rch & Prof#=BURNSRN,Main            , 3
Up Type= 0
Dn Type= 3
Dn Slope=0.0012
Boundary for River Rch & Prof#=BURNSRN,Main            , 4
Up Type= 0
Dn Type= 3
Dn Slope=0.0012
Boundary for River Rch & Prof#=BURNSRN,Main            , 5
Up Type= 0
Dn Type= 3
Dn Slope=0.0012
Boundary for River Rch & Prof#=BURNSRN,Main            , 6
Up Type= 0
Dn Type= 3
Dn Slope=0.0012
Boundary for River Rch & Prof#=BURNSRNT1,Main            , 1
Up Type= 0
Dn Type= 3
Dn Slope=0.00496
Boundary for River Rch & Prof#=BURNSRNT1,Main            , 2
Up Type= 0
Dn Type= 3
Dn Slope=0.00496
Boundary for River Rch & Prof#=BURNSRNT1,Main            , 3
Up Type= 0
Dn Type= 3
Dn Slope=0.00496
Boundary for River Rch & Prof#=BURNSRNT1,Main            , 4
Up Type= 0
Dn Type= 3
Dn Slope=0.00496
Boundary for River Rch & Prof#=BURNSRNT1,Main            , 5
Up Type= 0
Dn Type= 3
Dn Slope=0.00496
Boundary for River Rch & Prof#=BURNSRNT1,Main            , 6
Up Type= 0
Dn Type= 3
Dn Slope=0.00496
Boundary for River Rch & Prof#=CLBRSNCKT1,Main            , 1
Up Type= 0
Dn Type= 3
Dn Slope=0.00848
Boundary for River Rch & Prof#=CLBRSNCKT1,Main            , 2
Up Type= 0
Dn Type= 3
Dn Slope=0.00848
Boundary for River Rch & Prof#=CLBRSNCKT1,Main            , 3
Up Type= 0
Dn Type= 3
Dn Slope=0.00848
Boundary for River Rch & Prof#=CLBRSNCKT1,Main            , 4
Up Type= 0
Dn Type= 3
Dn Slope=0.00848
Boundary for River Rch & Prof#=CLBRSNCKT1,Main            , 5
Up Type= 0
Dn Type= 3
Dn Slope=0.00848
Boundary for River Rch & Prof#=CLBRSNCKT1,Main            , 6
Up Type= 0
Dn Type= 3
Dn Slope=0.00848
Boundary for River Rch & Prof#=CLBRSNCKT2,Main            , 1
Up Type= 0
Dn Type= 3
Dn Slope=0.00274
Boundary for River Rch & Prof#=CLBRSNCKT2,Main            , 2
Up Type= 0
Dn Type= 3
Dn Slope=0.00274
Boundary for River Rch & Prof#=CLBRSNCKT2,Main            , 3
Up Type= 0
Dn Type= 3
Dn Slope=0.00274
Boundary for River Rch & Prof#=CLBRSNCKT2,Main            , 4
Up Type= 0
Dn Type= 3
Dn Slope=0.00274
Boundary for River Rch & Prof#=CLBRSNCKT2,Main            , 5
Up Type= 0
Dn Type= 3
Dn Slope=0.00274
Boundary for River Rch & Prof#=CLBRSNCKT2,Main            , 6
Up Type= 0
Dn Type= 3
Dn Slope=0.00274
Boundary for River Rch & Prof#=INDIANCK,Main            , 1
Up Type= 0
Dn Type= 3
Dn Slope=0.00176
Boundary for River Rch & Prof#=INDIANCK,Main            , 2
Up Type= 0
Dn Type= 3
Dn Slope=0.00176
Boundary for River Rch & Prof#=INDIANCK,Main            , 3
Up Type= 0
Dn Type= 3
Dn Slope=0.00176
Boundary for River Rch & Prof#=INDIANCK,Main            , 4
Up Type= 0
Dn Type= 3
Dn Slope=0.00176
Boundary for River Rch & Prof#=INDIANCK,Main            , 5
Up Type= 0
Dn Type= 3
Dn Slope=0.00176
Boundary for River Rch & Prof#=INDIANCK,Main            , 6
Up Type= 0
Dn Type= 3
Dn Slope=0.00176
Boundary for River Rch & Prof#=LTROARCK,Main            , 1
Up Type= 0
Dn Type= 3
Dn Slope=0.04436
Boundary for River Rch & Prof#=LTROARCK,Main            , 2
Up Type= 0
Dn Type= 3
Dn Slope=0.04436
Boundary for River Rch & Prof#=LTROARCK,Main            , 3
Up Type= 0
Dn Type= 3
Dn Slope=0.04436
Boundary for River Rch & Prof#=LTROARCK,Main            , 4
Up Type= 0
Dn Type= 3
Dn Slope=0.04436
Boundary for River Rch & Prof#=LTROARCK,Main            , 5
Up Type= 0
Dn Type= 3
Dn Slope=0.04436
Boundary for River Rch & Prof#=LTROARCK,Main            , 6
Up Type= 0
Dn Type= 3
Dn Slope=0.04436
Boundary for River Rch & Prof#=MLGNCKTR5,Main            , 1
Up Type= 0
Dn Type= 3
Dn Slope=0.0247
Boundary for River Rch & Prof#=MLGNCKTR5,Main            , 2
Up Type= 0
Dn Type= 3
Dn Slope=0.0247
Boundary for River Rch & Prof#=MLGNCKTR5,Main            , 3
Up Type= 0
Dn Type= 3
Dn Slope=0.0247
Boundary for River Rch & Prof#=MLGNCKTR5,Main            , 4
Up Type= 0
Dn Type= 3
Dn Slope=0.0247
Boundary for River Rch & Prof#=MLGNCKTR5,Main            , 5
Up Type= 0
Dn Type= 3
Dn Slope=0.0247
Boundary for River Rch & Prof#=MLGNCKTR5,Main            , 6
Up Type= 0
Dn Type= 3
Dn Slope=0.0247
Boundary for River Rch & Prof#=ROARINGCK,Main            , 1
Up Type= 0
Dn Type= 3
Dn Slope=0.01435
Boundary for River Rch & Prof#=ROARINGCK,Main            , 2
Up Type= 0
Dn Type= 3
Dn Slope=0.01435
Boundary for River Rch & Prof#=ROARINGCK,Main            , 3
Up Type= 0
Dn Type= 3
Dn Slope=0.01435
Boundary for River Rch & Prof#=ROARINGCK,Main            , 4
Up Type= 0
Dn Type= 3
Dn Slope=0.01435
Boundary for River Rch & Prof#=ROARINGCK,Main            , 5
Up Type= 0
Dn Type= 3
Dn Slope=0.01435
Boundary for River Rch & Prof#=ROARINGCK,Main            , 6
Up Type= 0
Dn Type= 3
Dn Slope=0.01435
DSS Import GetInterval= 0
DSS Import GetPeak= 0
DSS Import FillOption= 0

--- BURNSRN.g01 (geometry) ---

Geom Title=Geometry
Program Version=5.07

River Reach=BURNSRN         ,Main
Reach XY= 30
2122829.76551279336223.1195715372123089.90213162336333.997630611
2123804.90201396337051.219949454 2123821.5686473337161.220057532
2123726.01306412337303.4422140272123881.56852728 337475.66431053
2123869.90188396338160.1088077872124057.67972362338434.553140789
2124254.90209821338930.1089081912124737.67967597339052.331104696
2124610.45748946339150.1087962842124717.12427089339261.219794527
2124668.23526105339427.8864559532124337.67981979339677.331167027
 2123656.5686492340031.219894946 2123734.3463808340086.775558114
2123740.45758903340206.7756461952123846.56859729340249.553119704
2123728.23517254340363.9977726942123635.45747095340341.219931111
2123569.90182778340500.664494112 2123724.3464008340720.664382204
 2123766.5687573340989.5532801152123709.90187588341121.220011532
2123283.79085147341447.330907866 2123442.1241962341810.108725622
2123385.45764288 341987.886585282123300.45748478  342022.3310702
2123213.23521829342368.9976996932123424.43591139342322.623120531

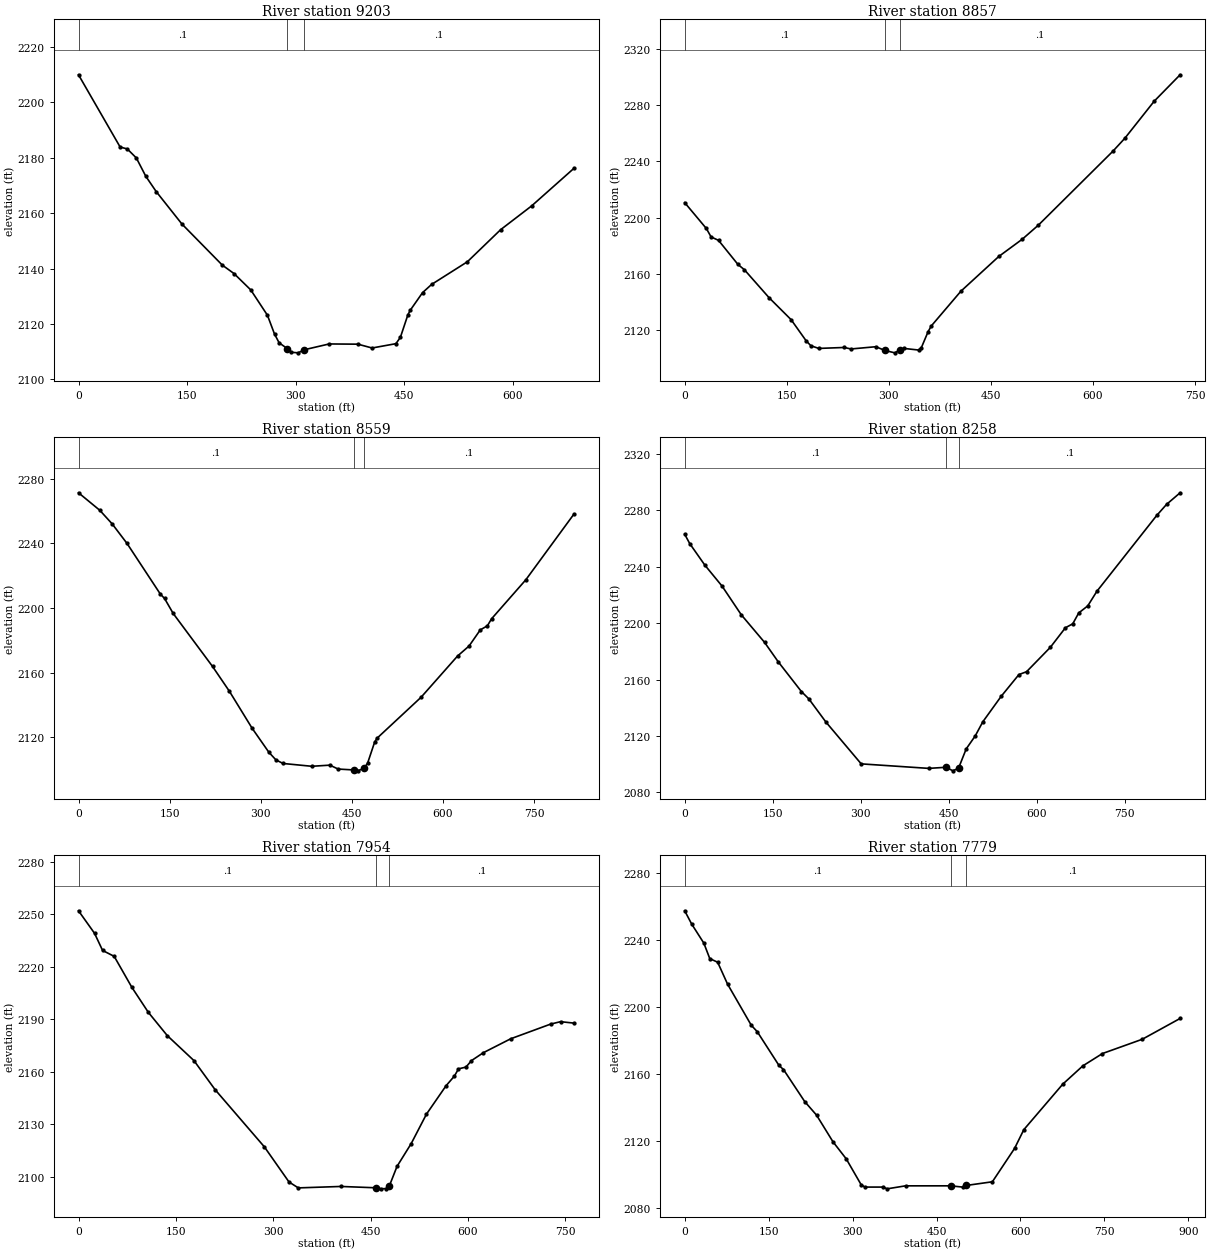
Type RM Length L Ch R = 1 ,9203    ,333.6,346.4,351.1
XS GIS Cut Line= 3
2122840.81306288336520.1754078722122839.64114922336221.549036622
2122867.24772128335836.759451866
#Sta/Elev= 30
       0 2209.99    57.5  2183.9    67.4  2183.2    79.9 2179.95      93 2173.32
   107.3 2167.82   142.8 2156.11   198.6 2141.26   214.9 2138.18     238 2132.28
     261 2123.14   270.8 2116.34   277.2 2113.17  288.512111.083   293.9 2109.77
   303.5 2109.56  311.712110.665   346.3 2112.77   385.9 2112.69   405.6 2111.31
   438.5 2112.87   444.7 2115.18   454.9 2123.18   458.2  2124.9   475.3  2131.3
   487.8 2134.27   537.2 2142.45   583.2 2154.05     626 2162.63   684.4 2176.19
#Mann= 3 ,-1 , 0
       0      .1       0  288.51    .045       0  311.71      .1       0
Bank Sta=288.51,311.71
XS Rating Curve= 0 ,0
Exp/Cntr=0.3,0.1

Type RM Length L Ch R = 1 ,8857    ,298.3,297.5,296.8
XS GIS Cut Line= 3
2122873.10466495336547.2586870342123082.81093845336369.762979031
2123422.41294953336069.642844364
#Sta/Elev= 30
       0 2210.68    31.8 2192.25    38.8 2186.23    49.7 2183.81    78.3 2166.61
    87.7 2162.88   124.1 2142.88   156.4 2127.28   178.4 2112.27   185.4 2108.72
     197 2106.81   234.3 2107.48   244.4 2106.42   280.9 2108.02   294.32105.329
   308.8 2103.66  315.87 2105.66   322.7 2106.78   343.6 2105.66   347.5 2107.04
   357.7 2118.76   362.4 2122.84   405.8 2147.53   461.5  2172.3   496.2 2184.67
   519.7 2194.63   629.5 2247.44   646.7 2256.49   689.9 2282.93     728 2301.77
#Mann= 3 ,-1 , 0
       0      .1       0   294.3    .045       0  315.87      .1       0
Bank Sta=294.3,315.87
XS Rating Curve= 0 ,0
Exp/Cntr=0.3,0.1

Type RM Length L Ch R = 1 ,8559    ,302,301.4,300.8
XS GIS Cut Line= 3
2122986.64643264336875.3836869452123295.94404238336580.232046276
2123567.89658245336303.508518368
#Sta/Elev= 30
       0 2271.31      35 2260.49    55.6 2251.98    79.9 2239.95   134.7 2208.63
   141.7 2205.88   155.9  2196.6   220.6 2163.84   248.4 2148.46   285.6 2125.69
   313.4  2110.7     325 2105.99   336.7 2103.78     384 2102.04   413.8 2102.74
   427.4 2100.33  453.612099.758   459.6 2099.22  469.912100.782   475.8 2103.88
   487.4 2116.91   491.2 2119.32     564 2144.79     624 2170.29   642.9 2176.47
   661.4 2186.47     673 2188.95     680 2193.34   736.4 2217.49   815.5  2258.1
#Mann= 3 ,-1 , 0
       0      .1       0  453.61    .045       0  469.91      .1       0
Bank Sta=453.61,469.91
XS Rating Curve= 0 ,0
Exp/Cntr=0.3,0.1

Type RM Length L Ch R = 1 ,8258    ,300.6,304.4,307.4
XS GIS Cut Line= 3
2123254.35488671337101.4252296092123531.60203561336765.356019869
2123793.93812513336452.466881871
#Sta/Elev= 30
       0 2263.16     8.5 2256.57    34.3 2241.26    63.8 2226.29    96.4 2206.02
     136  2186.5   159.3 2172.71   198.9 2151.54   211.4 2146.42   240.5    2130
   300.7 2100.29   415.6  2097.1  445.472097.878   456.9 2095.35  466.612097.325
   479.6 2110.93   494.9 2120.08   507.9 2130.14   539.1 2148.17   569.4 2163.63
   582.4 2165.65     623 2182.99   648.6 2196.83   661.1 2199.63   671.3 2207.35
   686.7 2212.35   702.1 2222.63   804.1 2276.45   820.9 2284.33     844 2292.56
#Mann= 3 ,-1 , 0
       0      .1       0  445.47    .045       0  466.61      .1       0
Bank Sta=445.47,466.61
XS Rating Curve= 0 ,0
Exp/Cntr=0.3,0.1

Type RM Length L Ch R = 1 ,7954    ,166.6,175,185.4
XS GIS Cut Line= 3
2123353.06203836337227.3258964422123735.64493462336980.823108613
2123999.14637613336821.216800526
#Sta/Elev= 30
       0 2251.95    24.7  2239.1    37.1 2229.32      55 2225.93    82.2 2208.27
   107.6 2193.98   136.8  2180.7   177.9 2166.43   210.4 2149.88   286.4 2117.19
   324.3 2097.17   338.6  2093.8   404.2 2094.62  458.712093.849   466.5 2093.26
     474 2093.44  478.822094.864   490.7 2106.08   512.5 2119.06   536.1 2135.92
   566.2 2152.07   579.1 2157.62   585.4 2161.73   596.9 2162.74   605.4 2166.44
   623.7 2170.96   665.9 2178.91   727.2 2187.26   742.6 2188.66   763.2 2187.84
#Mann= 3 ,-1 , 0
       0      .1       0  458.71    .045       0  478.82      .1       0
Bank Sta=458.71,478.82
XS Rating Curve= 0 ,0
Exp/Cntr=0.3,0.1

Type RM Length L Ch R = 1 ,7779    ,230.4,227.8,225.4
XS GIS Cut Line= 4
2123365.80237528337247.5298149112123640.08582998337137.988938347
2123809.14104106337120.7384066052124225.74138264337174.215055006
#Sta/Elev= 30
       0 2257.36    12.4 2249.46    34.2 2238.02    44.8 2228.79    58.9  2226.6
    76.6 2213.52     119 2188.92   129.6 2185.12   168.5 2164.91   176.5 2162.49
   214.4 2143.37   235.6 2135.23   264.9 2119.33   288.6 2109.12   315.4 2093.59
     322 2092.22     355 2092.22   361.6 2091.17   394.6 2092.96   475.12092.969
   496.9 2092.21   503.3  2093.2   549.8 2095.39   589.5 2115.34     606 2126.53
   675.5  2153.7   711.4 2164.65   746.6 2172.05   817.7 2180.57   885.3 2193.01
#Mann= 3 ,-1 , 0
       0      .1       0   475.1    .045       0   503.3      .1       0
Bank Sta=475.1,503.3
XS Rating Curve= 0 ,0
Exp/Cntr(USF)=0,0
Exp/Cntr=0.3,0.1

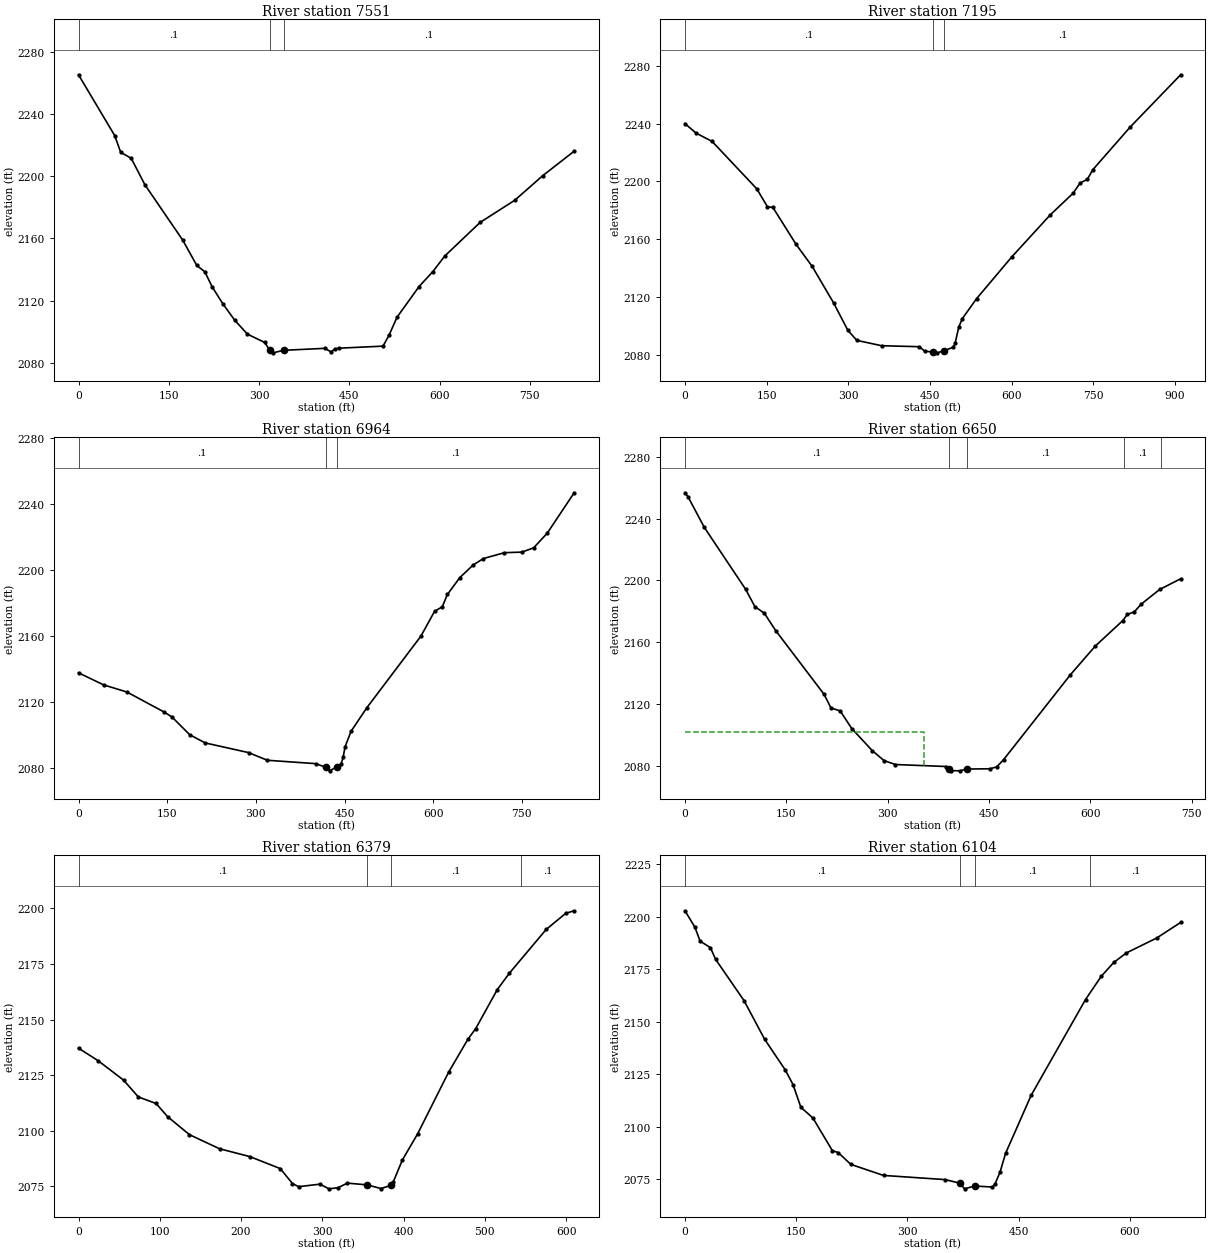
Type RM Length L Ch R = 1 ,7551    ,353,355.5,355.2
XS GIS Cut Line= 3
2123400.69481713337373.9860361962123857.28773597 337295.71585153
2124213.72960839337242.050276443
#Sta/Elev= 30
       0 2265.09    60.1 2226.04    70.1 2215.26    87.6 2211.41   110.3 2194.42
   173.3 2158.74   196.6 2142.51   209.9 2138.48     222 2128.87   239.8 2117.92
   259.8 2107.23   280.8 2098.39   309.3 2093.05  317.712088.226   323.1 2086.37
     3412088.007   409.6 2089.26   419.6 2086.98   426.2 2088.94   432.9 2089.36
     506 2090.68   515.9 2097.57   529.2 2109.18   565.7 2128.87   588.9 2138.62
   608.8 2148.65   667.4  2170.2     725 2184.45   771.2 2200.15   823.7 2215.99
#Mann= 3 ,-1 , 0
       0      .1       0  317.71    .045       0     341      .1       0
Bank Sta=317.71,341
XS Rating Curve= 0 ,0
Exp/Cntr=0.3,0.1

Type RM Length L Ch R = 1 ,7195    ,230.5,231.5,232.2
XS GIS Cut Line= 3
2123397.05473253337613.1335237772123851.98065996337602.835644111
2124306.96268964337593.812696278
#Sta/Elev= 30
       0 2239.92    20.2  2233.4    49.8 2227.62   131.8 2194.84   151.5 2182.32
   161.3    2182     204 2156.38   233.5 2141.16   272.9 2115.88   299.2 2096.81
   315.6 2089.97   360.9 2086.26   430.4 2085.58   440.3 2082.45  456.262081.844
   463.2 2081.33  476.382082.917   492.8 2085.23   496.1 2088.02   502.6 2099.03
   509.2 2104.97   535.4 2118.82   599.9 2147.65   670.7 2176.78   712.6 2191.75
   725.4 2198.77   738.9 2201.43   748.7 2207.97   817.6  2237.6   910.1 2273.72
#Mann= 3 ,-1 , 0
       0      .1       0  456.26    .045       0  476.38      .1       0
Bank Sta=456.26,476.38
XS Rating Curve= 0 ,0
Exp/Cntr=0.3,0.1

Type RM Length L Ch R = 1 ,6964    ,317.9,313.6,310
XS GIS Cut Line= 3
2123437.68818146337792.0501606912123629.35479286337818.091775283
2124273.10481772337859.758686692
#Sta/Elev= 30
       0 2137.77    42.3 2130.47      82  2126.1   144.9 2113.96   158.2 2110.94
   188.2 2100.18   214.3 2095.24   287.6 2089.38   319.5 2084.72   401.7 2082.66
  417.872080.482   424.7 2078.31  437.89 2080.88   444.5 2082.61   447.7 2086.71
     451  2092.9   460.9 2102.19   487.4 2116.41   579.3 2160.05   602.3 2175.04
   615.4 2177.83     624 2185.27   645.1 2195.54     668 2203.27     685 2207.08
   720.6 2210.63   749.9 2210.96   769.9 2213.55     793 2222.47   838.5 2246.96
#Mann= 3 ,-1 , 0
       0      .1       0  417.87    .045       0  437.89      .1       0
Bank Sta=417.87,437.89
XS Rating Curve= 0 ,0
Exp/Cntr=0.3,0.1

Type RM Length L Ch R = 1 ,6650    ,275.5,271,269
XS GIS Cut Line= 3
2123475.18810645338253.5085553682123852.66405755338145.850962281
2124182.47967088338058.716950193
#Sta/Elev= 30
       0  2256.7     4.6 2254.05    28.5 2234.42    89.9 2194.23   103.5 2183.09
   117.4 2178.89   134.2 2167.66   205.9 2126.42   216.1  2117.6   229.8 2115.69
   246.8 2104.32   277.5 2089.91   294.6 2083.57   311.6 2081.03   386.7 2079.75
  390.542078.445   393.5 2077.12   407.1 2076.95  417.322078.111   451.2 2078.28
   461.4 2079.47   471.6 2084.17   570.6 2139.11   607.3 2157.57     648 2174.05
   654.8 2178.08     665 2179.68   675.3 2184.68   702.6 2194.19   733.7  2201.1
#Mann= 5 ,-1 , 0
       0      .1       0  390.54    .045       0  417.32      .1       0
  650.43      .1       0  704.48      .1       0
#XS Ineff= 2 , 0
          353.59 2101.82
Permanent Ineff=
       F       F
Bank Sta=390.54,417.32
XS Rating Curve= 0 ,0
Exp/Cntr=0.3,0.1

Type RM Length L Ch R = 1 ,6379    ,272.7,275.5,278.6
XS GIS Cut Line= 3
2123694.97966161338543.0919657052123965.67498636338394.506961033
2124228.31324062 338247.25856787
#Sta/Elev= 30
       0 2137.14    23.8  2131.6    55.4 2122.82    73.6 2115.24    95.4  2112.3
   109.7 2106.35   136.5 2098.28   173.5 2091.96   210.9 2088.42   248.3 2083.03
   263.3  2076.3   270.8 2074.91     297 2076.04   308.2 2073.94   319.5 2074.46
   330.8 2076.52   355.52075.703   372.2 2074.07  384.072075.472   387.2 2076.95
   398.5  2086.9   417.3 2098.67   455.3 2126.28   479.1 2141.14   488.8 2145.99
   515.3 2163.47   530.1 2170.81   575.5 2190.52   599.6 2197.76   609.9 2198.89
#Mann= 4 ,-1 , 0
       0      .1       0   355.5    .045       0  384.07      .1       0
  543.96      .1       0
Bank Sta=355.5,384.07
XS Rating Curve= 0 ,0
Exp/Cntr=0.3,0.1

Type RM Length L Ch R = 1 ,6104    ,262.9,262,258.4
XS GIS Cut Line= 3
2123749.14654803338731.6335833672123862.68798763338691.008664608
2124389.77157912338541.008636534
#Sta/Elev= 30
       0 2202.92    13.4 2195.09    20.4 2188.44    34.3 2185.36    41.3 2179.78
    79.6 2160.14   107.5 2141.64   135.1 2127.15   145.7 2120.12   156.3 2109.29
   172.6 2104.13   198.8  2088.6   206.8 2087.64   223.7 2082.05   267.8 2076.78
   350.9  2074.8  370.452073.131   377.2 2070.39  390.622071.734   414.7 2071.25
   418.2 2072.65     425 2078.39   432.5 2087.33     467    2115   540.3 2160.61
   561.4 2171.64   578.4 2178.29   595.5 2182.85   636.5 2189.97   668.6 2197.36
#Mann= 4 ,-1 , 0
       0      .1       0  370.45    .045       0  390.62      .1       0
  546.65      .1       0
Bank Sta=370.45,390.62
XS Rating Curve= 0 ,0
Exp/Cntr=0.3,0.1

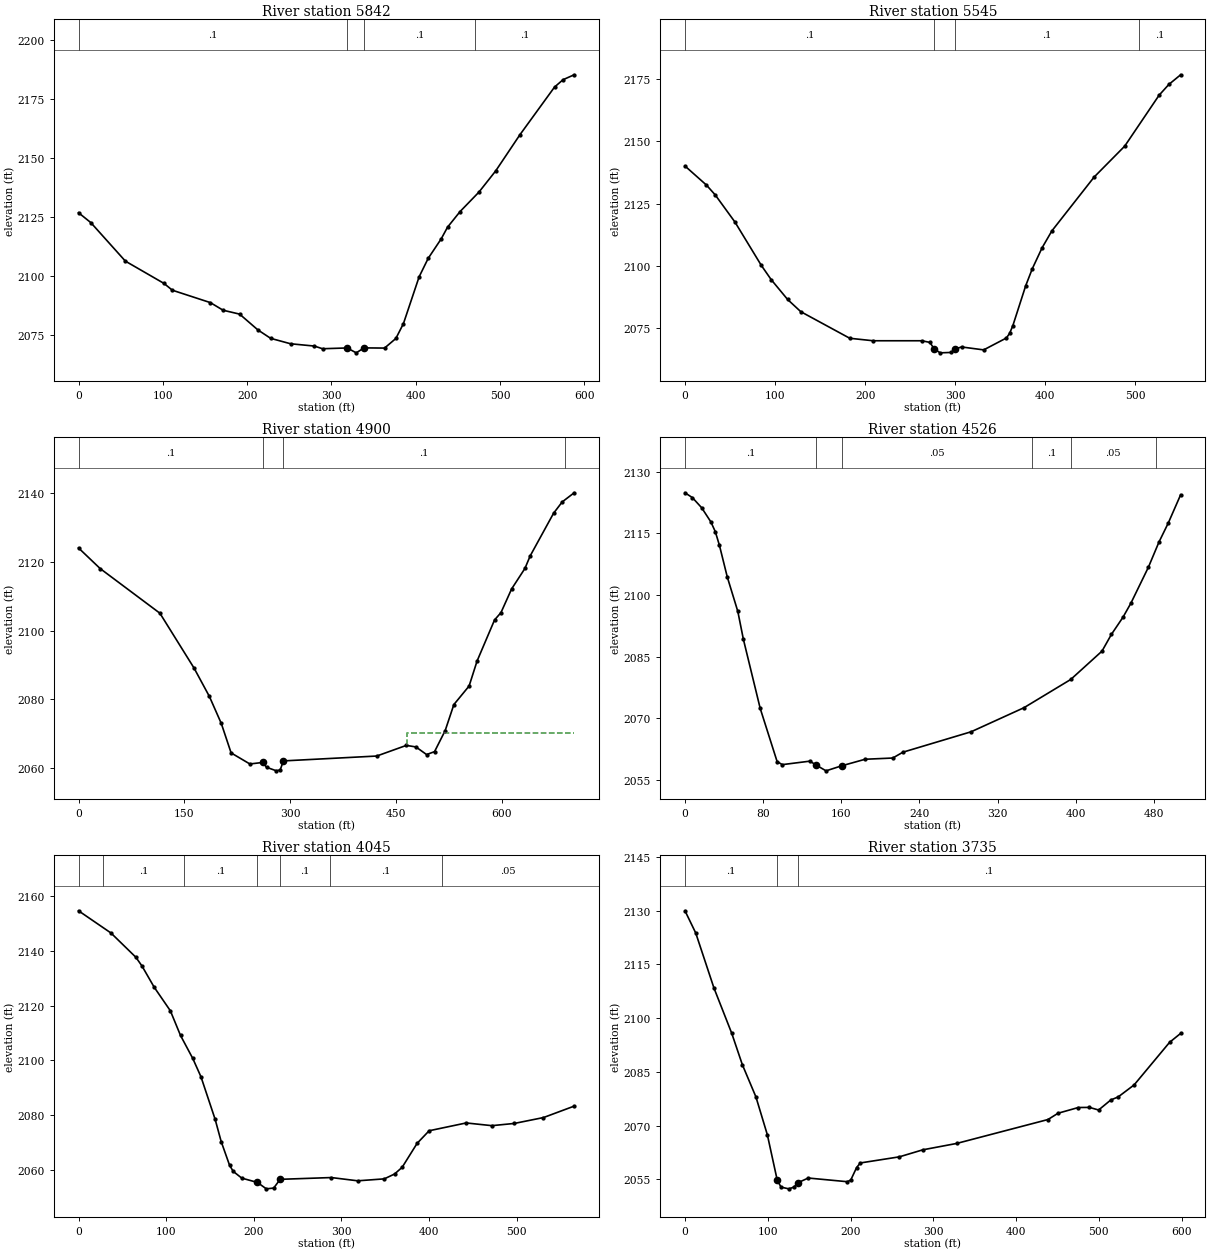
Type RM Length L Ch R = 1 ,5842    ,298.1,296.3,284.8
XS GIS Cut Line= 3
2123930.39651361339003.5086957812124215.20663953338844.018201113
2124444.97980204338719.133608371
#Sta/Elev= 30
       0 2126.83    14.6 2122.63    55.6 2106.29   101.4 2096.84   111.3 2093.96
   156.4  2088.7   171.5 2085.47   191.1 2083.82   212.8 2077.11   227.9 2073.55
   251.5 2071.25   279.8 2070.27   289.4 2069.14   318.7 2069.47   329.4  2067.4
   338.72069.501     363 2069.42   376.4 2073.49   385.4  2079.8     404 2099.64
   414.7 2107.44   430.2 2115.75   437.7 2120.69   452.6 2127.33     475 2135.59
   494.9  2144.6   523.5 2159.87   564.6 2180.11   574.7 2183.24   587.9 2185.33
#Mann= 4 ,-1 , 0
       0      .1       0   318.7    .045       0   338.7      .1       0
  470.43      .1       0
Bank Sta=318.7,338.7
XS Rating Curve= 0 ,0
Exp/Cntr=0.3,0.1

Type RM Length L Ch R = 1 ,5545    ,629.2,645.3,635
XS GIS Cut Line= 3
2124278.31314063339264.9668342772124364.77130103339089.966856197
2124512.68799996338767.050179198
#Sta/Elev= 30
       0 2140.11    23.8 2132.44    33.6 2128.46    55.5 2117.52    84.7 2100.09
    95.7 2094.33     114 2086.31   128.6  2081.4     183 2070.68     209 2069.68
   263.1 2069.68     272 2069.01  276.662066.416   283.4 2064.81   295.6 2064.97
  299.762066.306   307.1 2067.18   331.7    2066   356.9 2070.79   360.5 2072.66
   364.1 2075.79   378.4  2091.9   385.7 2098.73   396.6 2107.18   407.4 2113.95
   454.3 2135.64   488.3 2148.12   526.5 2168.65   537.3 2172.98   550.4 2176.88
#Mann= 4 ,-1 , 0
       0      .1       0  276.66    .045       0  299.76      .1       0
  504.58      .1       0
Bank Sta=276.66,299.76
XS Rating Curve= 0 ,0
Exp/Cntr=0.3,0.1

Type RM Length L Ch R = 1 ,4900    ,347,374.4,396.9
XS GIS Cut Line= 4
2124458.52144164339379.5502665342124636.64641345  339282.6751322
 2124821.0213728339103.5084957782124940.81312796 338892.05025728
#Sta/Elev= 30
       0 2124.11    30.7  2118.1   115.4  2105.1   163.8 2089.14   185.6 2080.86
   202.5 2072.99   216.4 2064.42     243  2061.2  261.342061.644   266.6 2060.24
   280.7  2059.2     286 2059.48  290.632062.093   422.9 2063.51   464.9 2066.61
   478.5 2066.16   493.6 2063.94   504.9 2064.79     520 2070.93   532.3  2078.5
   553.9  2083.9   565.2 2091.17     590 2103.14   599.1 2105.28   614.2 2112.17
   633.1 2118.15   640.6 2121.82   673.7 2134.21   685.9  2137.5   702.9 2140.17
#Mann= 4 ,-1 , 0
       0      .1       0  261.34    .045       0  290.63      .1       0
  689.25      .1       0
#XS Ineff= 1 ,-1
  465.42  702.89  2070.3
Permanent Ineff=
       F
Bank Sta=261.34,290.63
XS Rating Curve= 0 ,0
Exp/Cntr=0.3,0.1

Type RM Length L Ch R = 1 ,4526    ,475.2,480.7,471.2
XS GIS Cut Line= 2
2124465.81309372339396.2168998722124755.39650404339812.883717448
#Sta/Elev= 30
       0 2124.91     7.6 2123.73    17.1 2121.26    26.5 2117.82    31.1 2115.41
    35.3 2112.08    43.3 2104.41    54.1 2096.01    59.8 2089.22      77 2072.41
    94.3 2059.47    99.6 2058.71   127.9 2059.56  134.222058.612   144.4  2057.2
  160.412058.424   184.4 2060.02   212.7 2060.32   223.1 2061.74   292.9 2066.71
     347 2072.57   394.9 2079.45   426.9 2086.35   436.6 2090.45   448.4 2094.61
   456.5 2098.03   474.4 2106.78   485.2  2112.9   494.8 2117.57   507.4 2124.42
#Mann= 6 ,-1 , 0
       0      .1       0  134.22    .045       0  160.41     .05       0
  355.21      .1       0   395.2     .05       0  481.89      .1       0
Bank Sta=134.22,160.41
XS Rating Curve= 0 ,0
Exp/Cntr=0.3,0.1

Type RM Length L Ch R = 1 ,4045    ,309.3,310,312.7
XS GIS Cut Line= 3
2124024.49376637339578.5088581142124195.32708612339751.425507039
2124401.57700172339999.342005953
#Sta/Elev= 30
       0 2154.64      37 2146.54    65.4 2137.69    72.4  2134.5    86.3 2126.77
   104.8 2118.14   116.4 2109.13   130.4 2100.73   139.7 2094.08   155.9 2078.53
   162.8 2070.41   172.3 2061.82   176.5 2059.53   186.3 2057.06  204.182055.484
   214.3 2053.15   222.7 2053.43  230.112056.622   288.5 2057.27   318.6 2056.08
   348.9 2056.79   360.7 2058.57   369.3 2061.01   386.4 2069.76   400.1 2074.35
   442.4  2077.2   471.7 2076.21   497.3 2077.02   530.6 2079.17   565.6 2083.34
#Mann= 7 ,-1 , 0
       0      .1       0   28.04      .1       0  120.92      .1       0
  204.18    .045       0  230.11      .1       0  287.15      .1       0
  414.31     .05       0
Bank Sta=204.18,230.11
XS Rating Curve= 0 ,0
Exp/Cntr=0.3,0.1

Type RM Length L Ch R = 1 ,3735    ,236.9,236.1,235.3
XS GIS Cut Line= 3
2123822.41018105339766.0084831122123976.57686746339966.008739278
2124254.70196739340172.258654863
#Sta/Elev= 30
       0 2129.99      13 2123.78      35 2108.42    56.5 2095.76    69.3    2087
    85.7    2078    99.5 2067.42   111.52054.683   116.1 2052.78   125.5 2052.31
   131.7  2052.8  136.452054.018   148.9 2055.33   196.2  2054.3   200.3 2054.79
   207.4 2058.27   211.8 2059.54     259 2061.25   287.3 2063.21   328.2 2064.99
   438.5 2071.67   450.7 2073.43   475.2 2075.03   488.7 2075.06   499.7 2074.33
   514.5 2077.15   523.3 2077.98   542.6 2081.34   585.5 2093.25   598.8 2095.73
#Mann= 3 ,-1 , 0
       0      .1       0   111.5    .045       0  136.45      .1       0
Bank Sta=111.5,136.45
XS Rating Curve= 0 ,0
Exp/Cntr=0.3,0.1

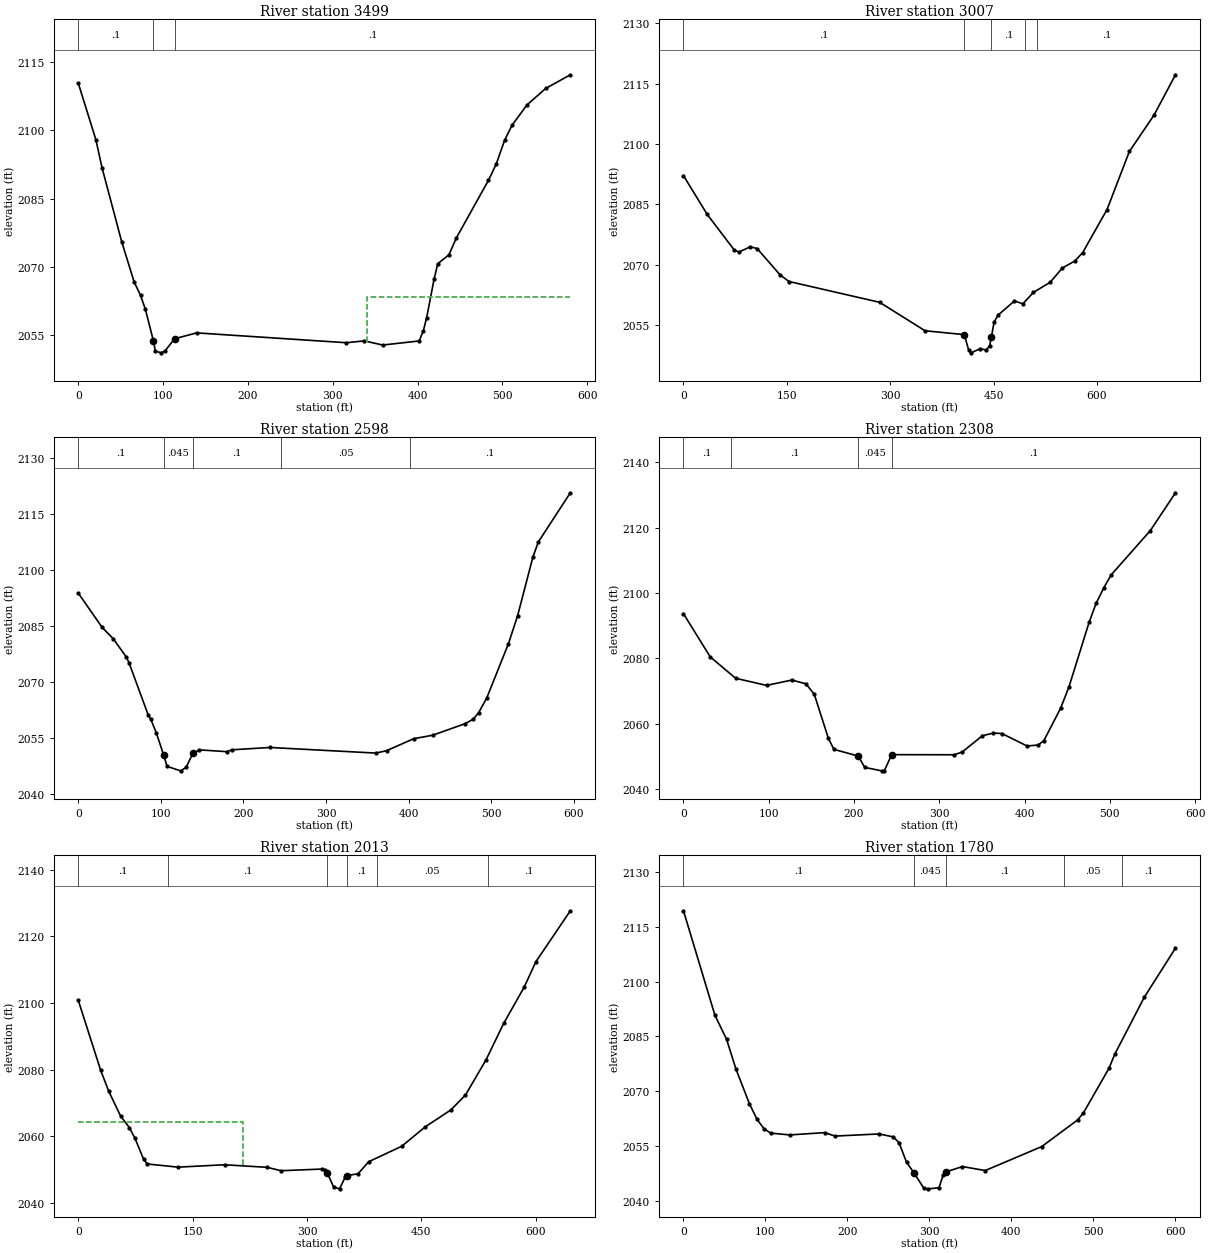
Type RM Length L Ch R = 1 ,3499    ,466.9,492.2,484.1
XS GIS Cut Line= 2
2123632.82689878339914.9668466152124017.20211428340349.341962114
#Sta/Elev= 30
       0 2110.39    20.7 2097.97    27.9 2091.82    51.2 2075.42    65.8  2066.6
    73.3 2063.65    79.1 2060.53   88.482053.619    90.8 2051.35    97.7 2050.96
   102.3  2051.4   113.42054.069   139.5 2055.36   316.1 2053.19   337.1  2053.6
   358.8 2052.68   401.8 2053.58   406.8 2055.87   410.6  2058.7   419.4 2067.23
   423.7 2070.61   436.9 2072.59   445.6 2076.29   483.5 2089.02   492.8 2092.67
   502.6 2097.88   511.4 2101.19   528.9 2105.64     551 2109.28     580 2112.29
#Mann= 3 ,-1 , 0
       0      .1       0   88.48    .045       0   113.4      .1       0
#XS Ineff= 2 , 0
                          340.58         2063.28
Permanent Ineff=
       F       F
Bank Sta=88.48,113.4
XS Rating Curve= 0 ,0
Exp/Cntr=0.3,0.1

Type RM Length L Ch R = 1 ,3007    ,400.2,408.3,387.7
XS GIS Cut Line= 4
2123399.49370405340159.758679867 2123613.0352717340181.633636117
 2123860.9520987340362.8836016952124035.95207679340442.050110027
#Sta/Elev= 30
       0 2092.15    34.2 2082.57    73.9 2073.62    80.5 2073.18      97 2074.47
   106.9 2074.03   139.9 2067.54   153.1 2065.85   284.6 2060.68   350.5 2053.61
  407.422052.658   413.7 2048.86   417.3 2048.13   430.1 2049.14   439.5 2048.84
   444.2 2049.95  446.622051.952   450.6 2055.75   456.2 2057.47   480.2 2061.02
   492.4  2060.3   507.6 2063.13   532.1 2065.67   549.7 2069.21   567.7 2070.93
   579.1    2073   614.5 2083.73   646.9 2098.15   682.6 2107.17   713.8  2117.2
#Mann= 5 ,-1 , 0
       0      .1       0  407.42    .045       0  446.62      .1       0
  495.97     .05       0  513.26      .1       0
Bank Sta=407.42,446.62
XS Rating Curve= 0 ,0
Exp/Cntr=0.3,0.1

Type RM Length L Ch R = 1 ,2598    ,283.1,290.6,288.5
XS GIS Cut Line= 3
2123444.28528112340511.8419651992123615.11860088340510.800300613
2124040.11873513340509.758636028
#Sta/Elev= 30
       0 2093.86    28.8  2084.7    42.3 2081.66    58.3 2076.69    61.6 2075.09
    84.5 2061.29    87.8 2060.04    94.4 2056.46  103.152050.591   107.5 2047.44
   123.9 2046.25   130.5 2047.16   138.62050.916   146.6 2051.87   179.7 2051.39
   186.2 2051.89   232.2 2052.51   360.1 2051.01   373.2 2051.64   406.1 2054.86
     429 2055.79   468.4 2058.89   478.2 2060.08   484.8 2061.86   494.6 2065.78
   520.9 2080.35     532 2087.86   550.4 2103.49     557 2107.57   595.8 2120.77
#Mann= 5 ,-1 , 0
       0      .1       0  103.15    .045       0   138.6      .1       0
  245.82     .05       0  401.39      .1       0
Bank Sta=103.15,138.6
XS Rating Curve= 0 ,0
Exp/Cntr=0.3,0.1

Type RM Length L Ch R = 1 ,2308    ,283.6,294.9,294.5
XS GIS Cut Line= 4
2123497.41017488340721.2168745252123646.36853838340734.758514121
2123747.41033104340737.8835078632124073.45200178340752.466812029
#Sta/Elev= 30
       0 2093.71    31.5 2080.46    61.2 2073.94    97.4 2071.77   127.1  2073.4
   143.6 2072.25   153.4 2069.06   169.8 2055.66   176.4 2052.18  205.012050.136
   212.5 2046.67   232.4 2045.61   235.5 2045.61  244.142050.568   317.6 2050.53
     327 2051.39   350.4 2056.34   363.5 2057.18   373.4 2057.03     403 2053.21
   416.1 2053.52   422.7 2054.89   442.4 2064.83   452.2 2071.42   475.7 2091.08
   484.1    2097   492.9 2101.61   501.5 2105.57   547.5 2119.15     577 2130.73
#Mann= 4 ,-1 , 0
       0      .1       0   55.32      .1       0  205.01    .045       0
  244.14      .1       0
Bank Sta=205.01,244.14
XS Rating Curve= 0 ,0
Exp/Cntr=0.3,0.1

Type RM Length L Ch R = 1 ,2013    ,229.8,232.9,233.6
XS GIS Cut Line= 3
2123467.20190197340839.9669651092123718.24372271340980.592011943
 2124023.4521018341167.050300449
#Sta/Elev= 30
       0 2100.76    29.3 2079.81    39.9 2073.51    55.6    2066    66.9 2062.63
    74.4 2059.35    85.7 2053.06    90.5 2051.68   130.8 2050.73   191.8 2051.45
   247.4 2050.68   266.2 2049.66   319.5 2050.16   323.4 2049.96  326.762048.916
   334.9 2044.74   342.6 2044.22   350.2 2047.74  352.772048.206   366.9 2048.74
     381 2052.37   424.2    2057   455.2 2062.85   488.7 2067.91   507.8 2072.37
   534.8 2082.93   557.9 2093.86   584.8 2104.74   600.2  2112.4   645.4 2127.69
#Mann= 6 ,-1 , 0
       0      .1       0  117.96      .1       0  326.76    .045       0
  352.77      .1       0  391.24     .05       0   537.2      .1       0
#XS Ineff= 2 , 0
           215.9 2064.25
Permanent Ineff=
       F       F
Bank Sta=326.76,352.77
XS Rating Curve= 0 ,0
Exp/Cntr=0.3,0.1

Type RM Length L Ch R = 1 ,1780    ,389.7,387.1,374.9
XS GIS Cut Line= 3
2123375.53541863340964.9670431912123575.53534672341118.092065036
2123822.41018105 341363.92523478
#Sta/Elev= 30
       0 2119.48    38.4 2090.81    52.6 2084.22    64.1 2076.01    80.5 2066.54
    89.7 2062.29      98 2059.76   106.2  2058.5   129.7    2058   172.4 2058.63
   184.8 2057.68   238.5 2058.27     256 2057.46     263 2055.86   272.2 2050.49
  281.192047.605   293.1 2043.44   298.4 2043.21   311.7  2043.5     317 2047.08
  320.262047.856   340.3 2049.32   368.2 2048.23     437 2054.79     481 2062.12
     488 2064.05   519.3 2076.33   526.3 2080.17   562.2 2095.74   600.3 2109.24
#Mann= 5 ,-1 , 0
       0      .1       0  281.19    .045       0  320.26      .1       0
  464.18     .05       0  535.21      .1       0
Bank Sta=281.19,320.26
XS Rating Curve= 0 ,0
Exp/Cntr=0.3,0.1