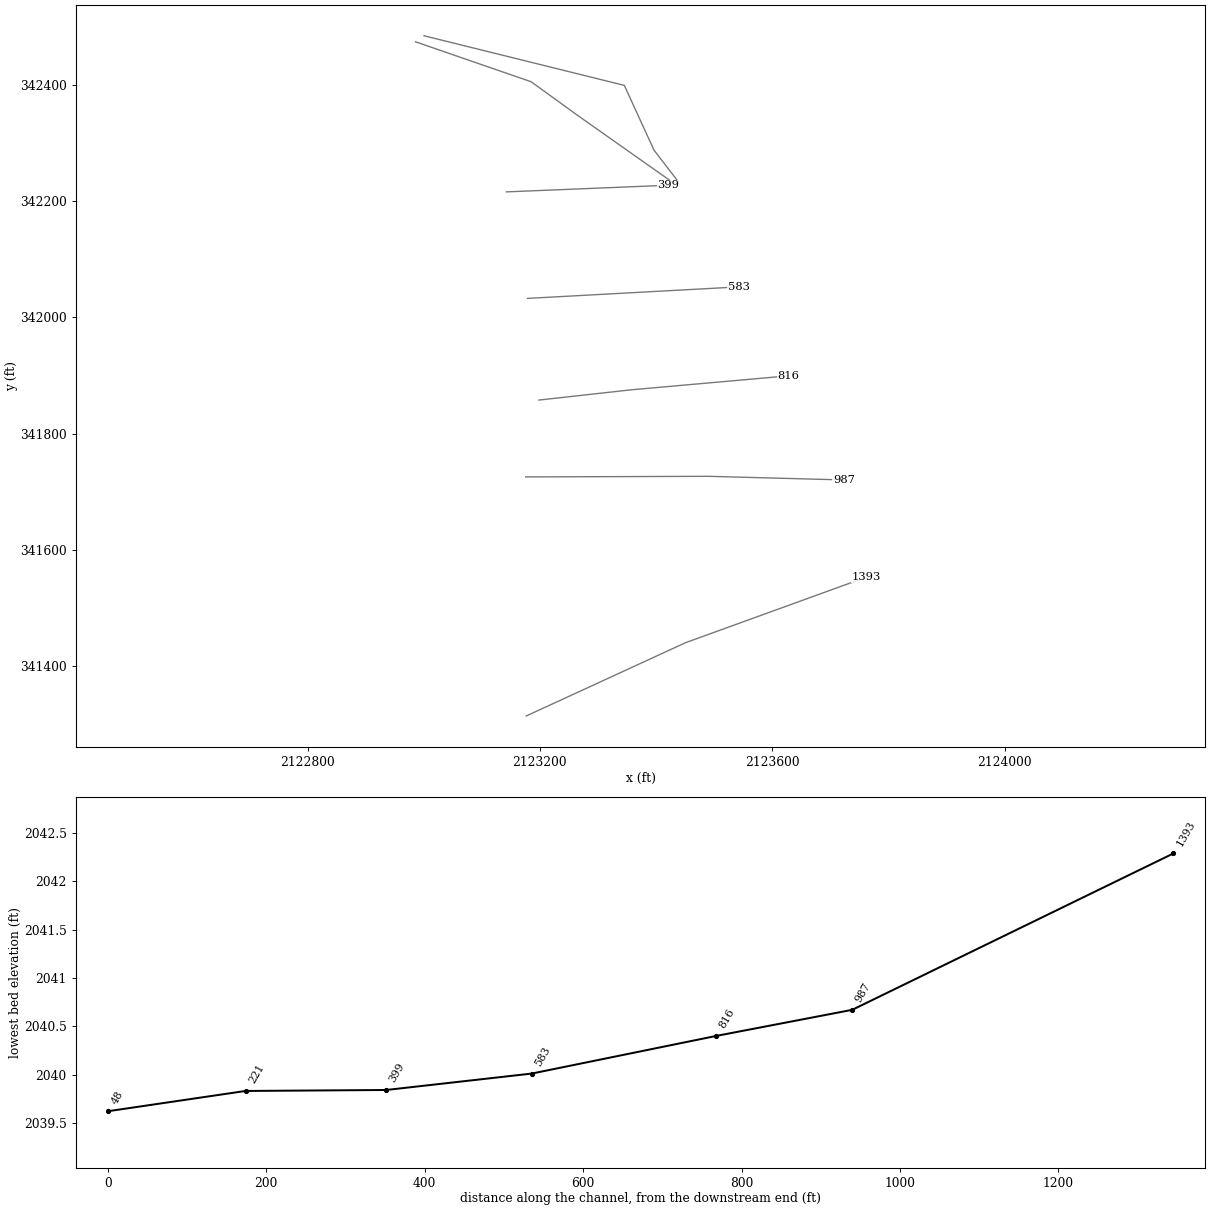
HEC-RAS study BURNSRN.prj: BURNSRN

--- BURNSRN.g01 (geometry) --- (continued)

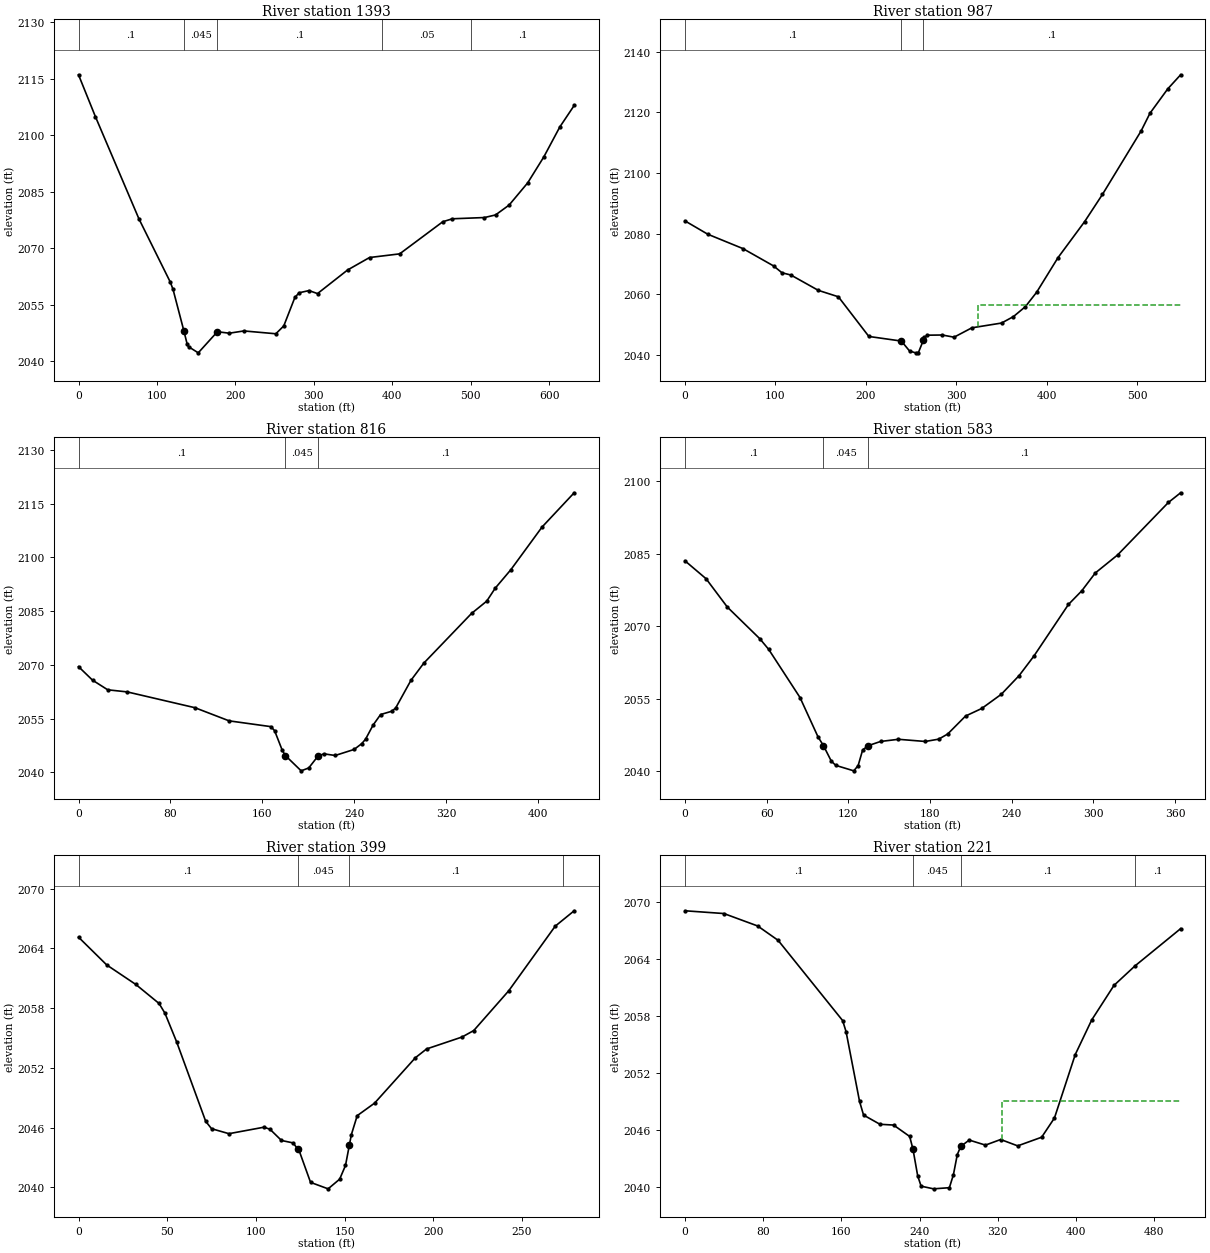
Type RM Length L Ch R = 1 ,1393    ,414.6,405.6,388.8
XS GIS Cut Line= 3
2123176.57682705341313.9253347812123450.53526863341439.967077449
2123760.95197064341552.466852441
#Sta/Elev= 30
       0 2116.07    21.5 2104.98    77.1  2077.8   116.9 2061.09   120.5  2059.1
  134.392048.032   138.5 2044.58   140.2 2043.92   152.6 2042.29     1772047.893
   192.1  2047.5   210.8  2048.1   251.5 2047.35   261.6 2049.43   275.8 2057.01
   281.2 2058.23   293.8 2058.81   304.6 2058.01   342.9 2064.27   370.9 2067.58
   409.3 2068.55   464.3 2077.08   476.5 2077.86   517.4 2078.19   531.5 2078.88
   548.8  2081.5   572.5  2087.4     593 2094.27   613.4 2102.22   631.7 2107.92
#Mann= 5 ,-1 , 0
       0      .1       0  134.39    .045       0     177      .1       0
  386.87     .05       0  500.03      .1       0
Bank Sta=134.39,177
XS Rating Curve= 0 ,0
Exp/Cntr=0.3,0.1

Type RM Length L Ch R = 1 ,987     ,166.7,171.6,170.1
XS GIS Cut Line= 3
2123175.53516245341725.3835013662123490.11852279341726.425165951
2123723.45204562341720.175178453
#Sta/Elev= 30
       0 2084.16    25.2 2079.77    64.1 2075.03      98 2069.31   107.2 2067.07
   117.1 2066.32   147.4 2061.27   169.6 2059.15   203.3 2046.07  239.222044.553
   248.3 2041.28   254.9 2040.67   258.1 2040.78  263.682044.897   264.7 2045.73
     268 2046.49   284.4 2046.55   297.5 2045.83   317.2 2048.92     350 2050.49
   363.2 2052.63   376.3 2055.88   388.8 2060.64   412.4 2072.04   441.9 2083.94
   461.6 2092.91   504.3 2113.81   514.1 2119.65   533.8  2127.7     548 2132.33
#Mann= 3 ,-1 , 0
       0      .1       0  239.22    .045       0  263.68      .1       0
#XS Ineff= 2 , 0
                           323.6         2056.58
Permanent Ineff=
       F       F
Bank Sta=239.22,263.68
XS Rating Curve= 0 ,0
Exp/Cntr=0.3,0.1

Type RM Length L Ch R = 1 ,816     ,226.7,233,226.7
XS GIS Cut Line= 3
2123198.45211136341857.6752315312123357.82712072341875.383529454
2123627.61857587341899.341814861
#Sta/Elev= 30
       0  2069.5    12.2 2065.72    25.4 2063.03    42.4 2062.44   101.3 2058.03
     131 2054.36   167.4 2052.74   170.6 2051.61   177.2 2046.18  179.942044.677
   193.7  2040.4   200.3 2041.21  208.262044.484   213.4 2045.15   223.3 2044.69
   239.8 2046.38   246.4    2048   249.7 2049.23   256.3 2053.19   262.8 2056.12
   272.7 2057.06     276    2058   289.2 2065.67   300.4 2070.48   341.9 2084.35
   355.1 2087.78   362.5  2091.4   376.1 2096.56   403.3  2108.5   431.2 2118.05
#Mann= 3 ,-1 , 0
       0      .1       0  179.94    .045       0  208.26      .1       0
Bank Sta=179.94,208.26
XS Rating Curve= 0 ,0
Exp/Cntr=0.3,0.1

Type RM Length L Ch R = 1 ,583     ,183.8,183.8,183.5
XS GIS Cut Line= 2
2123178.66048428342032.6752096122123542.20208004342052.466836706
#Sta/Elev= 30
       0 2083.55    15.5 2079.84    31.1 2073.97      55 2067.39    61.5 2065.19
    84.5 2055.21    97.7 2047.07  101.682045.254   107.5 2042.02   110.8 2041.14
     124 2040.01   127.2  2041.1   130.5 2044.33  134.482045.221   143.7  2046.1
   156.8 2046.55   176.5  2046.1   186.4 2046.58     193 2047.65   206.1 2051.37
     218 2052.94   232.4 2055.89   245.5 2059.77   256.3  2063.8   281.7 2074.51
   291.5 2077.34   301.4 2081.03   317.8 2084.77   355.1 2095.65   364.1 2097.66
#Mann= 3 ,-1 , 0
       0      .1       0  101.68    .045       0  134.48      .1       0
Bank Sta=101.68,134.48
XS Rating Curve= 0 ,0
Exp/Cntr=0.3,0.1

Type RM Length L Ch R = 1 ,399     ,189.5,177.5,151.6
XS GIS Cut Line= 2
 2123142.2018958342216.008504361 2123421.3686603342227.466814786
#Sta/Elev= 30
       0 2065.12    15.9 2062.33    32.3 2060.37    45.4 2058.46    48.7 2057.49
    55.3 2054.61    71.7 2046.62      75 2045.88    84.8 2045.38   104.5 2046.03
   107.9 2045.83   114.4  2044.7     121 2044.45  123.462043.861   124.3 2043.71
   130.8 2040.49   140.7 2039.84   147.2 2040.81   150.5 2042.19   152.7 2044.25
   153.8 2045.28   157.1 2047.19   166.9 2048.45   189.9 2053.01   196.2 2053.89
   216.2 2055.09   222.8 2055.74   242.5 2059.73   268.7 2066.22   279.4 2067.77
#Mann= 4 ,-1 , 0
       0      .1       0  123.46    .045       0   152.7      .1       0
  273.09      .1       0
Bank Sta=123.46,152.7
XS Rating Curve= 0 ,0
Exp/Cntr=0.3,0.1

Type RM Length L Ch R = 1 ,221     ,185.1,173.8,159.4
XS GIS Cut Line= 4
2122985.95188022342474.341977194 2123184.9104718342405.591786608
2123264.07698011342348.3002345262123426.57698321342233.716802284
#Sta/Elev= 30
       0 2069.08    39.8 2068.79    74.4 2067.48    95.3 2065.97   161.3 2057.53
   164.8 2056.37   178.6 2049.03   182.7 2047.59   199.5 2046.62   213.4 2046.54
   229.9 2045.34   233.32043.977   238.1 2041.19   241.6 2040.11   254.3 2039.83
   270.5 2039.95   274.6  2041.3   278.6 2043.43  282.162044.297   290.8 2044.96
   307.4 2044.43     323 2045.02   340.4 2044.35   364.9 2045.26     378 2047.28
   399.3 2053.96   416.1 2057.59   438.9 2061.23   460.4 2063.28   507.1  2067.2
#Mann= 4 ,-1 , 0
       0      .1       0   233.3    .045       0  282.16      .1       0
   460.4      .1       0
#XS Ineff= 2 , 0
                          323.98         2049.05
Permanent Ineff=
       F       F
Bank Sta=233.3,282.16
XS Rating Curve= 0 ,0
Exp/Cntr=0.3,0.1

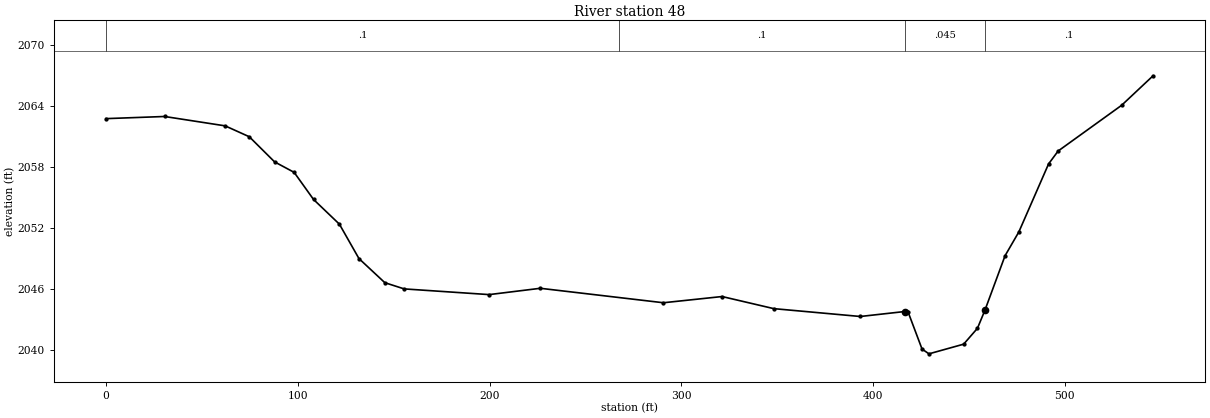
Type RM Length L Ch R = 1 ,48      ,53.42,47.56,41.69
XS GIS Cut Line= 4
2123000.53518438342484.758623034 2123345.3271457 342399.34179911
2123396.36871028342287.8836887032123438.03529364342233.716802284
#Sta/Elev= 30
       0 2062.73    30.5 2062.94    62.1 2062.02    74.7 2060.95    87.9 2058.48
    98.1 2057.45   108.2 2054.79   121.7 2052.36   131.9 2048.98   145.4 2046.61
   155.5    2046   199.8 2045.44   226.5 2046.06   290.7 2044.64   321.3 2045.25
   348.3 2044.06   393.4 2043.29  416.512043.776   418.4 2043.69   425.6 2040.09
   429.2 2039.62   447.3 2040.57   454.5 2042.13  458.452043.929   468.9 2049.26
   476.1  2051.6   491.6 2058.28   496.6 2059.55   529.7 2064.04   546.1 2066.94
#Mann= 4 ,-1 , 0
       0      .1       0  267.67      .1       0  416.51    .045       0
  458.45      .1       0
Bank Sta=416.51,458.45
XS Rating Curve= 0 ,0
Exp/Cntr=0.3,0.1
LCMann Table=0

Chan Stop Cuts=-1
Use User Specified Reach Order=0
Composite Channel Slope=5